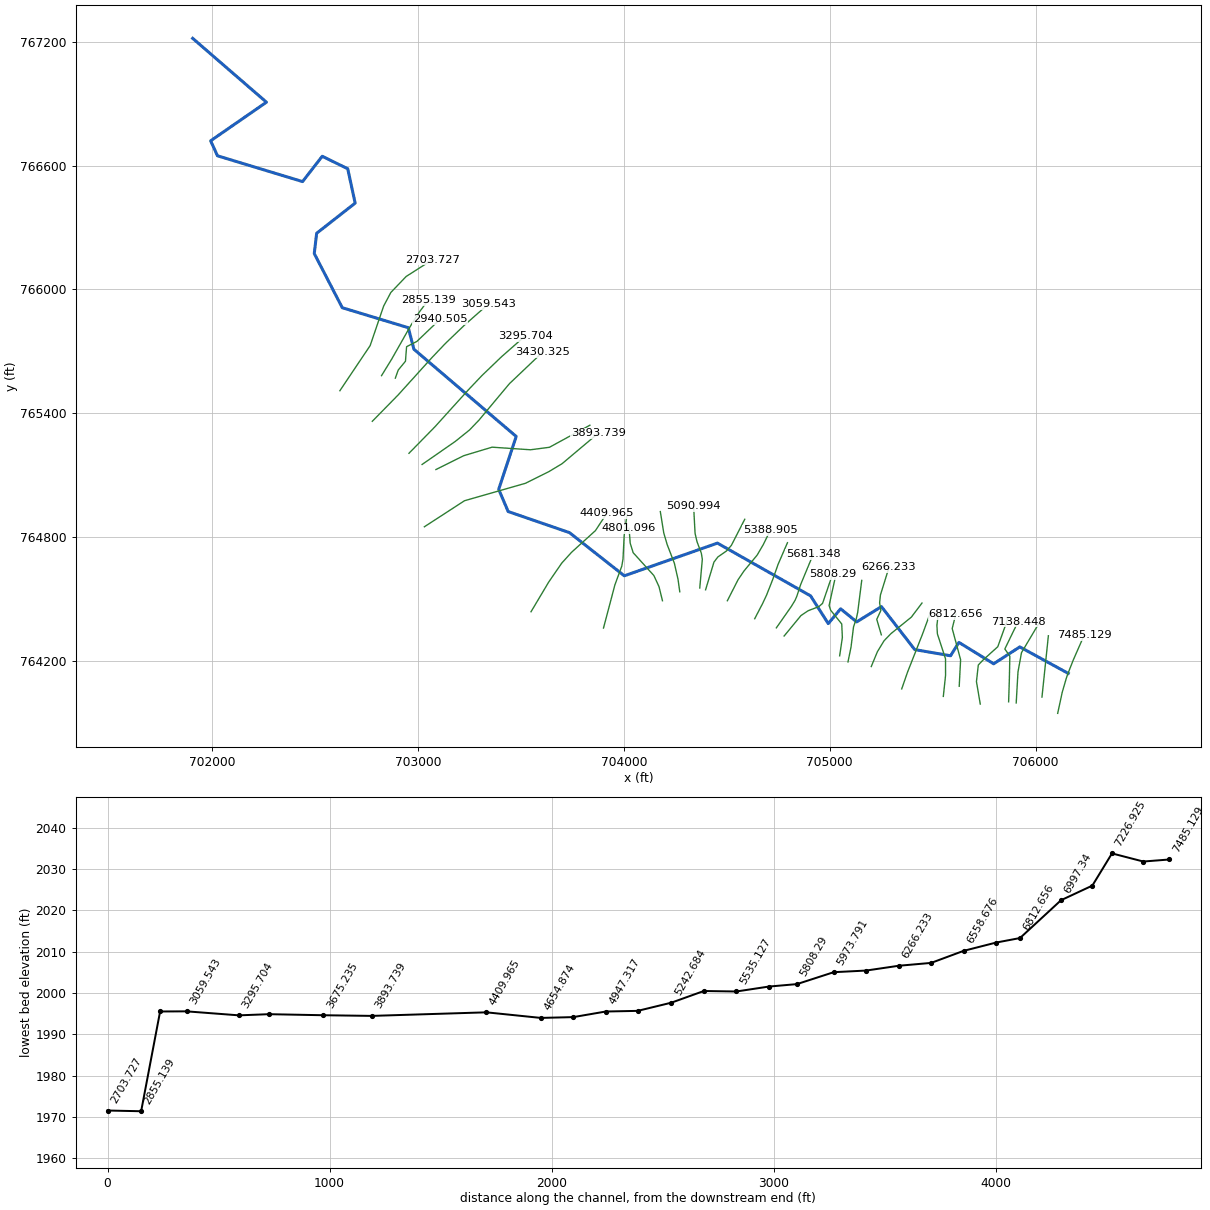
--- 14448_ras.prj (project) ---

Proj Title=14448
Current Plan=p01
Default Exp/Contr=0.3,0.1
English Units
Geom File=g01
Flow File=f01
Plan File=p01
Y Axis Title=Elevation
X Axis Title(PF)=Main Channel Distance
X Axis Title(XS)=Station
BEGIN DESCRIPTION:
RFD model 14448 exported to HEC-RAS
END DESCRIPTION:

--- 14448_ras.p01 (plan) ---

Plan Title=Plan 01
Program Version=4.10
Short Identifier=Plan 01
Geom File=g01
Flow File=f01
Subcritical Flow
Calc Critical at every XS
Secant Critical Depth

--- 14448_ras.f01 (steady flow) ---

Flow Title=Flow 01
Program Version=5.01
Number of Profiles= 6
Profile Names=10yr,25yr,50yr,100yr,100plus,500yr
River Rch & RM=14448,38,7485.129
  192.36  325.84  456.63  584.36  853.17 1543.34
River Rch & RM=14448,38,7226.925
  198.69  336.65  471.85   603.9   881.7 1587.84
River Rch & RM=14448,38, 6997.34
   199.6  338.19  474.02  606.68  885.76 1594.16
River Rch & RM=14448,38,6812.656
  212.44  360.09  504.86  646.28  943.57 1683.66
River Rch & RM=14448,38,6558.676
  218.35  370.17  519.07  664.52   970.2 1724.65
River Rch & RM=14448,38,6412.455
  223.65   379.2   531.8  680.86  994.05 1761.22
River Rch & RM=14448,38,6266.233
  232.41  394.15  552.86  707.91 1033.54 1821.52
River Rch & RM=14448,38,6120.012
  234.44  397.62  557.75  714.19 1042.71 1835.48
River Rch & RM=14448,38,5973.791
   235.6   399.6  560.54  717.77 1047.95 1843.43
River Rch & RM=14448,38, 5808.29
   238.5  404.54  567.51  726.72 1061.01 1863.26
River Rch & RM=14448,38,5681.348
  250.01  424.19  595.21  762.28 1112.93 1941.78
River Rch & RM=14448,38,5535.127
  256.57   435.4  611.01  782.58 1142.57 1986.37
River Rch & RM=14448,38,5388.905
     258  437.83  614.44  786.98 1148.99 1996.01
River Rch & RM=14448,38,5242.684
  266.22  451.86  634.22   812.4  1186.1 2051.57
River Rch & RM=14448,38,4947.317
   269.6  457.64  642.37  822.87 1201.39 2074.38
River Rch & RM=14448,38,4801.096
  272.13  461.96  648.47   830.7 1212.83 2091.43
River Rch & RM=14448,38,4654.874
   274.1  465.32  653.21  836.79 1221.71 2104.65
River Rch & RM=14448,38,4409.965
   476.3  811.34 1142.04 1465.35 2139.42 3415.27
River Rch & RM=14448,38,3893.739
  685.66 1170.27 1649.92 2118.93 3093.63 4695.33
River Rch & RM=14448,38,3675.235
  687.27 1173.04 1653.84 2123.97 3100.99 4704.97
River Rch & RM=14448,38,3430.325
  695.79 1187.64 1674.52 2150.58 3139.84 4755.75
River Rch & RM=14448,38,3295.704
  704.27  1202.2 1695.13 2177.11 3178.58 4806.32
River Rch & RM=14448,38,3059.543
  706.57 1206.14  1700.7 2184.28 3189.05 4819.96
River Rch & RM=14448,38,2940.505
  709.78 1211.64 1708.49  2194.3 3203.69 4839.02
River Rch & RM=14448,38,2703.727
   712.3 1215.97 1714.61 2202.18 3215.18 4853.97
River Rch & RM=14448,38,2552.316
  713.22 1217.54 1716.83 2205.04 3219.36 4859.41
Boundary for River Rch & Prof#=14448,38,1
Up Type= 0
Dn Type= 2
Boundary for River Rch & Prof#=14448,38,2
Up Type= 0
Dn Type= 2
Boundary for River Rch & Prof#=14448,38,2
Up Type= 0
Dn Type= 2
Boundary for River Rch & Prof#=14448,38,2
Up Type= 0
Dn Type= 2
Boundary for River Rch & Prof#=14448,38,2
Up Type= 0
Dn Type= 2
Boundary for River Rch & Prof#=14448,38,2
Up Type= 0
Dn Type= 2

--- 14448_ras.g01 (geometry) ---

Geom Title=14448
Program Version=4.10

River Reach=14448,38
Reach XY= 30
706158.682723105764138.483243361705923.420186162764266.841704398
705796.300112456764184.858468473705627.601872325764288.641015857
705586.839683115764223.901068315705412.822510421764253.806561247
705251.155843765 764462.13989456705130.662830502764388.148713037
705052.735115856764451.689772666704992.822510421764379.917672351
704906.711399287764514.362116784704454.210592717764770.093139783
704001.711399317764611.584338993703735.213080913764820.997807622
703437.371121526764923.285727888703391.364177078765030.924616799
703476.344885081765287.350684822 702979.24328649 765710.47655879
702952.200017244765814.643225461 702631.29473266 765911.65378347
702495.171939284766174.278777227 702506.83860594766272.612110555
702693.901900113766418.915657982702657.810828179766585.528777227
702533.921939284766646.084332794702438.366383761766523.306555018
702025.033050388766648.306555003701991.699717045766721.084332794
702262.810828179766908.306555003701904.405121535767217.943068296

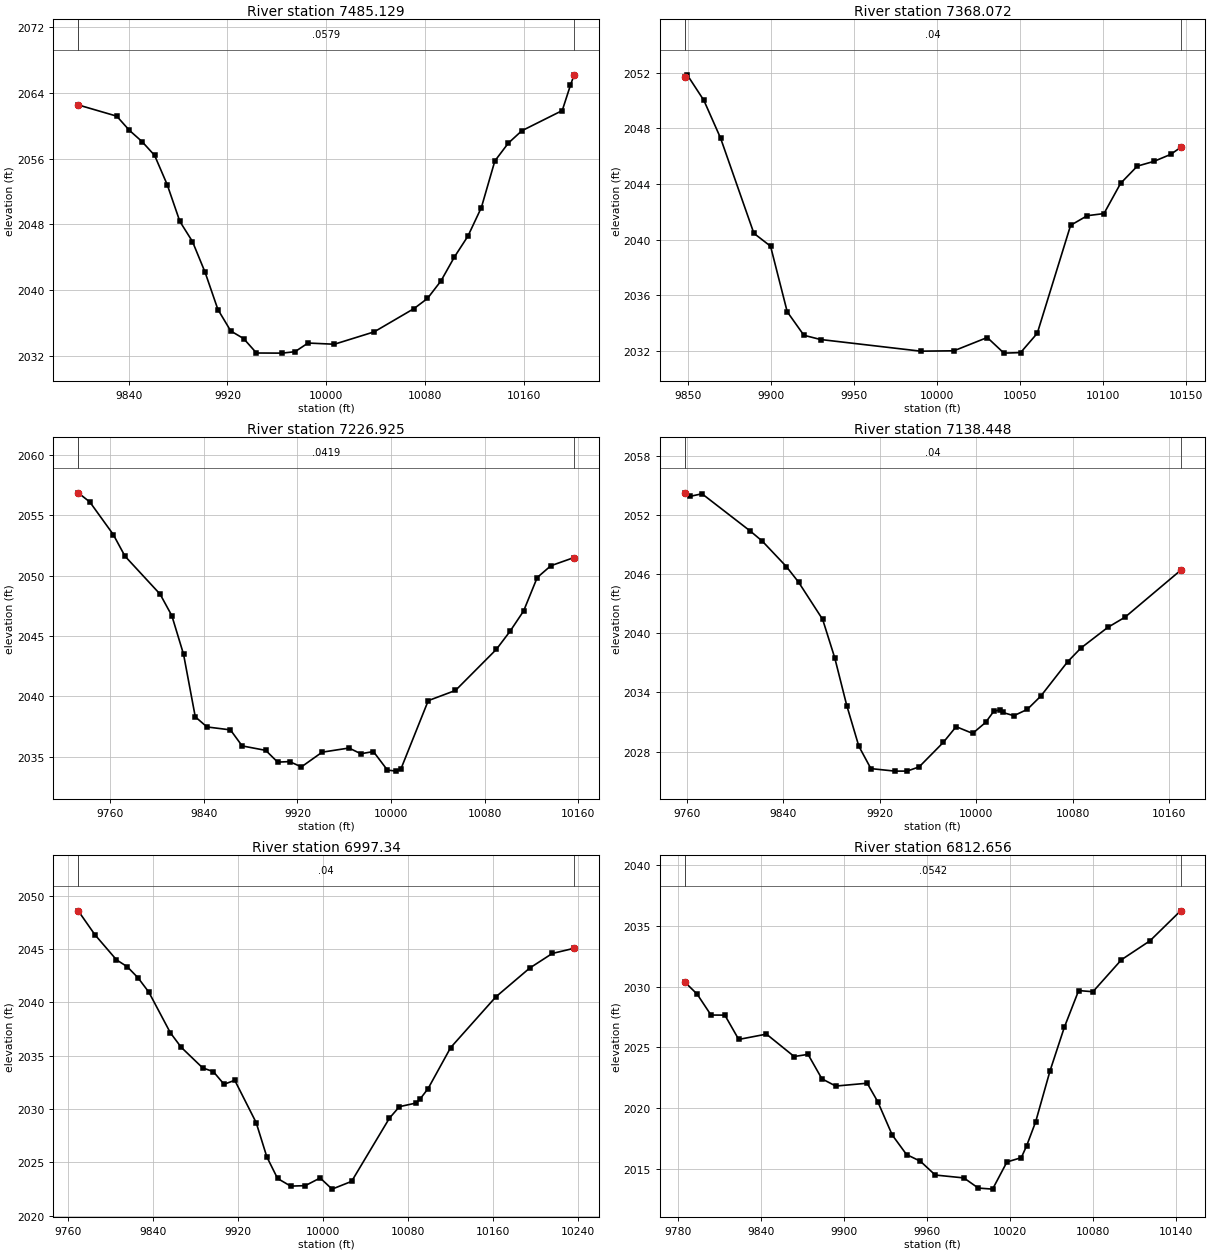
Type RM Length L Ch R = 1 ,7485.129,117.057700,117.057700,117.057700
XS GIS Cut Line= 6
706107.419578454763944.485316548706129.493705914764046.553064666
706150.420678177764118.304491736706158.094963541764139.769532091
706184.619674194  764206.4804604706236.212297666764323.841416212
#Sta/Elev= 30
9799.0362062.5479830.256 2061.189840.4872059.4589850.7182058.0919860.9492056.406
9871.1812052.8369881.4122048.3699891.6432045.9179901.8742042.1749912.2622037.644
9922.6792035.0349933.095 2034.119943.5122032.3549964.3452032.3399974.7622032.515
9985.3112033.56810006.63 2033.4210038.912034.927 10071.2 2037.76 10082.12038.993
10093.02 2041.1210103.942044.03910114.872046.57210125.792050.05910136.72 2055.73
10147.642057.89810158.562059.40110191.33 2061.8610197.982064.94610200.99 2066.21
#Mann= 3 , 0 , 0
9799.036  0.0579       09799.036  0.0579       010200.99  0.0579       0
#XS Ineff= 2 , 0
       0                               0
Bank Sta=9799.036,10200.99
Exp/Cntr=0.3,0.1

Type RM Length L Ch R = 1 ,7368.072,141.146900,141.146900,141.146900
XS GIS Cut Line= 2
706031.128828585764023.489500716706062.229094088764320.995813847
#Sta/Elev= 23
9847.9072051.6859849.4262051.834 9859.482049.9999869.5352047.2959889.6442040.451
9899.6982039.5249909.7532034.8159919.8072033.1279929.8622032.8229990.1892031.985
 10010.32032.01110030.412032.96610040.462031.84410050.522031.88210060.57 2033.27
10080.682041.02610090.732041.71710100.792041.86710110.842044.041 10120.92045.276
10130.952045.61810141.012046.11810147.032046.617
#Mann= 3 , 0 , 0
9847.907    0.04       09847.907    0.04       010147.03    0.04       0
#XS Ineff= 2 , 0
       0                               0
Bank Sta=9847.907,10147.03
Exp/Cntr=0.3,0.1

Type RM Length L Ch R = 1 ,7226.925,88.476900,88.476900,88.476900
XS GIS Cut Line= 4
705905.918147027763995.099517941705914.516652226764145.000000015
705931.710625708764239.206905782706022.905461192764392.119458169
#Sta/Elev= 30
9732.5912056.8769742.5072056.118 9762.542053.4229772.5572051.6289802.6062048.475
9812.6222046.6949822.6392043.4959832.6552038.3119842.6722037.4719862.7052037.229
9872.721  2035.99892.903 2035.539903.0682034.5569913.233  2034.69923.3982034.162
9941.1252035.3819964.0592035.7249974.224 2035.259984.9232035.4339996.8892033.897
10004.45 2033.8110008.532034.00610031.822039.65310055.112040.49910090.042043.903
10101.682045.39210113.322047.08110124.972049.85510136.612050.83210156.542051.515
#Mann= 3 , 0 , 0
9732.591  0.0419       09732.591  0.0419       010156.54  0.0419       0
#XS Ineff= 2 , 0
       0 9945.93                       0
Bank Sta=9732.591,10156.54
Exp/Cntr=0.3,0.1

Type RM Length L Ch R = 1 ,7138.448,141.107600,141.107600,141.107600
XS GIS Cut Line= 5
705869.071748853764000.626477674705872.756388694764113.929152012
 705875.00000003764221.955547929705850.648549765764256.708944917
705915.129746526 764389.35597828
#Sta/Elev= 30
9758.1972054.2539762.5722053.8949772.5782054.1559812.5992050.3749822.6042049.348
9842.6152046.759 9852.622045.196 9872.632041.4119882.6322037.5229892.6352032.671
9902.6372028.5469912.6392026.2729932.6432026.0179942.6452026.0219952.6472026.445
9972.6522028.9259983.3262030.5289997.0352029.84610007.752030.95410014.462032.071
10019.962032.25710022.042031.96710031.262031.64110042.382032.283 10053.5 2033.62
10075.742037.10410086.862038.507 10109.12040.59810123.492041.64110169.53 2046.39
#Mann= 3 , 0 , 0
9758.197    0.04       09758.197    0.04       010169.53    0.04       0
#XS Ineff= 2 , 0
       09969.113        10018.15       0
Bank Sta=9758.197,10169.53
Exp/Cntr=0.3,0.1

Type RM Length L Ch R = 1 , 6997.34,184.684300,184.684300,184.684300
XS GIS Cut Line= 6
705731.305677235763989.518480405705712.722914487764098.617280915
 705721.71457386764178.942771405705744.493444324764202.920529753
705816.426719397764267.660477296705865.581124008764404.333699927
#Sta/Elev= 30
 9769.452048.5689785.1542046.3289805.4422043.9759815.5862043.328 9825.732042.288
9835.8752040.9479856.1632037.1329866.3072035.7799886.5432033.8419896.6052033.491
9906.6672032.303 9916.732032.6829936.8552028.7179946.9172025.497 9956.982023.479
9969.3022022.7599983.0952022.8029997.0952023.52210008.282022.47610026.672023.204
10062.242029.12810071.652030.20810086.782030.535 10090.82030.883 10098.6  2031.9
10119.862035.74810162.36  2040.510194.242043.202 10215.52044.57210236.042045.056
#Mann= 3 , 0 , 0
 9769.45    0.04       0 9769.45    0.04       010236.04    0.04       0
#XS Ineff= 2 , 0
       0                               0
Bank Sta=9769.45,10236.04
Exp/Cntr=0.3,0.1

Type RM Length L Ch R = 1 ,6812.656,107.758400,107.758400,107.758400
XS GIS Cut Line= 4
705629.010974006764076.028253097705635.801861018764204.592396662
705594.958734244764355.897616327705612.595539004764426.444835305
#Sta/Elev= 30
9785.0132030.3949793.9982029.3929804.0122027.6679814.0262027.659 9824.042025.656
9844.0672026.0949864.0952024.2489874.1092024.4259884.123 2022.419894.1372021.814
9916.8342022.0489924.5372020.5089934.8952017.7859945.253 2016.179955.2052015.623
9965.9692014.4839986.6842014.2449997.0422013.409 10007.42013.32110017.762015.558
10028.122015.91310031.95 2016.8810038.472018.85710048.832023.04910059.19 2026.65
10069.552029.68310079.862029.58810100.482032.22510121.092033.786 10143.22036.254
#Mann= 3 , 0 , 0
9785.013  0.0542       09785.013  0.0542       0 10143.2  0.0542       0
#XS Ineff= 2 , 0
       0                               0
Bank Sta=9785.013,10143.2
Exp/Cntr=0.3,0.1

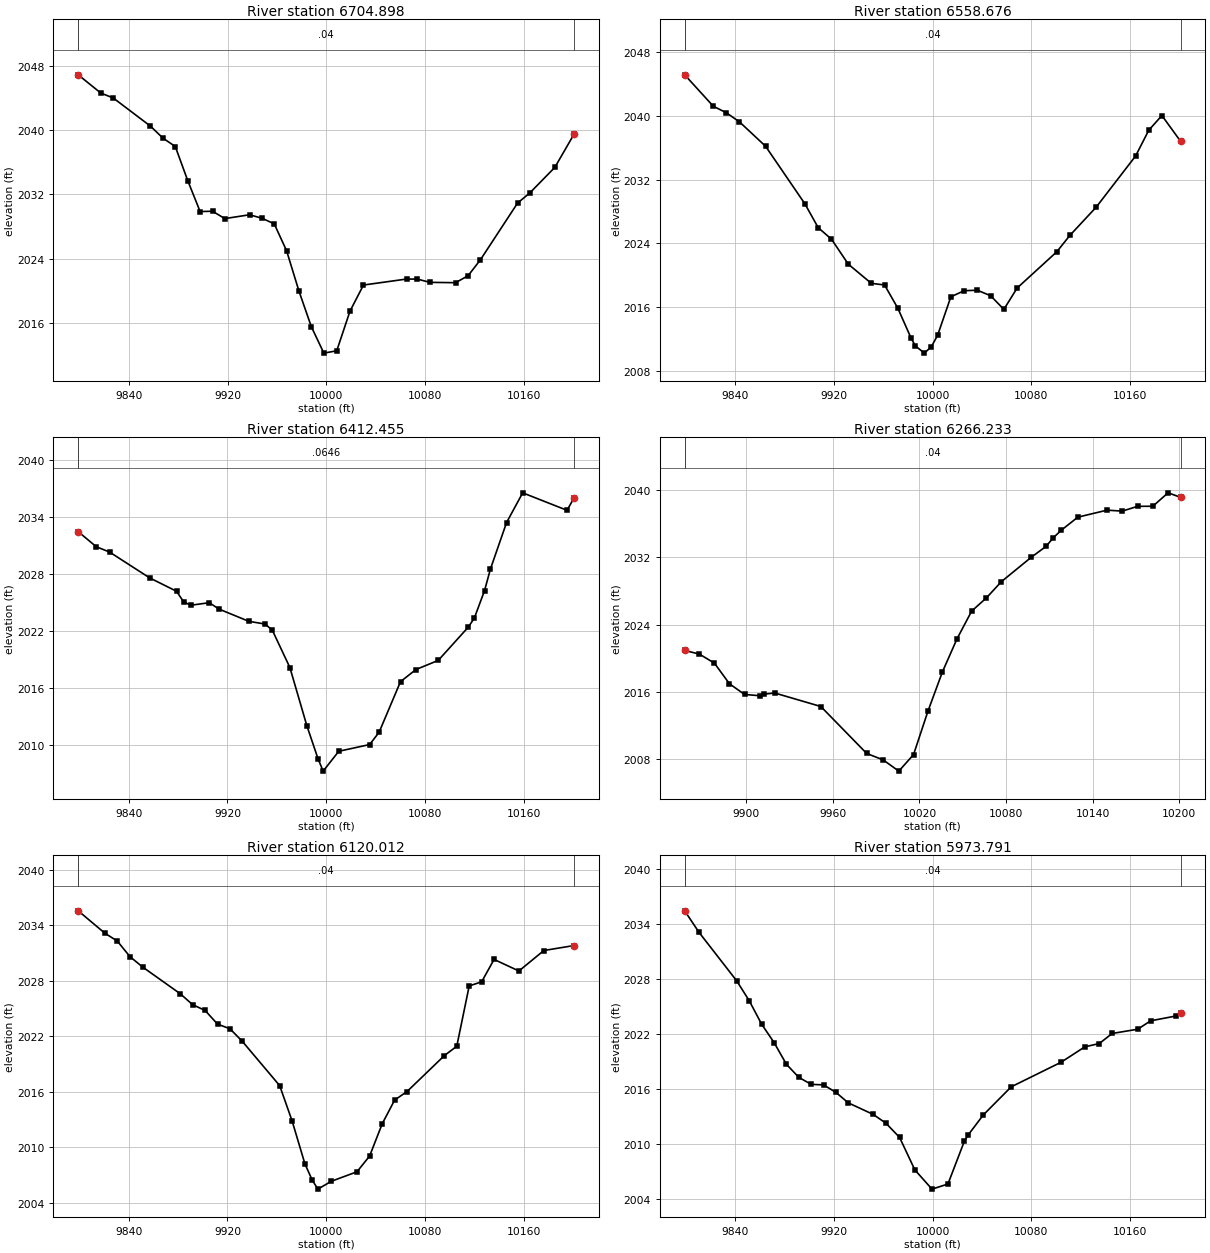
Type RM Length L Ch R = 1 ,6704.898,146.221400,146.221400,146.221400
XS GIS Cut Line= 6
705551.759743676 764026.80304367705562.697509338764129.284764497
705562.418052612764209.284164946 705522.83626912764330.427647609
705520.648880276764371.716549416705526.403064457 764420.53676211
#Sta/Elev= 30
9799.0492046.8759817.3492044.6069827.4062043.9949857.5772040.4859867.633    2039
 9877.692037.9469887.7472033.7129897.8042029.851 9907.83 2029.899917.8352028.976
9937.843 2029.459947.8482029.0239957.8552028.3179967.8612024.9619977.8682019.946
9987.9072015.5079998.0192012.22410008.462012.51410019.19 2017.4510030.122020.702
10065.172021.45110073.742021.43910084.052021.03610104.682020.99410114.862021.861
10124.87 2023.8510154.932030.902   101652032.18810185.142035.35410200.782039.513
#Mann= 3 , 0 , 0
9799.049    0.04       09799.049    0.04       010200.78    0.04       0
#XS Ineff= 2 , 0
       0                               0
Bank Sta=9799.049,10200.78
Exp/Cntr=0.3,0.1

Type RM Length L Ch R = 1 ,6558.676,146.221400,146.221400,146.221400
XS GIS Cut Line= 6
705349.576553869764063.105905339705378.379485608764145.672886987
 705419.79820268764250.309989027705420.457890167764252.198060111
705452.229419388764333.045890349 705491.21491033764439.242618206
#Sta/Elev= 30
9799.0172045.1789822.2052041.2359832.7962040.4119843.3872039.2759864.5692036.209
9896.4952028.966 9907.252025.9769918.0052024.5349931.6222021.3979950.2692018.989
9961.024 2018.789971.7792015.8629982.5342012.1019985.963 2011.139993.289 2010.22
    99992011.03610004.012012.45410014.75 2017.29 10025.52018.06110036.24 2018.12
10046.992017.42910057.732015.71610068.482018.396 10100.62022.94710111.252025.011
10132.562028.55510164.522034.98510175.172038.21910185.822040.06710200.992036.824
#Mann= 3 , 0 , 0
9799.017    0.04       09799.017    0.04       010200.99    0.04       0
#XS Ineff= 2 , 0
       0                               0
Bank Sta=9799.017,10200.99
Exp/Cntr=0.3,0.1

Type RM Length L Ch R = 1 ,6412.455,146.221400,146.221400,146.221400
XS GIS Cut Line= 6
705201.619274745764171.496554543705231.512546771764243.654494856
705264.068007025764296.955618835705297.940237511764331.719502484
 705396.44338852764411.173912898705448.169021543764479.602294137
#Sta/Elev= 30
9799.078 2032.469813.6942030.8789824.5182030.3149856.9912027.6029878.7162026.199
9884.4462025.0969890.1162024.7289905.2752024.9959913.1662024.3269937.3452023.039
 9950.442022.7569956.3052022.1229970.5792018.1879984.295 2012.099993.4272008.583
 9997.552007.30310010.182009.389 10035.22010.09410042.872011.38710060.212016.703
10072.722017.97610090.782018.93410114.99 2022.4110119.992023.36610128.272026.254
10133.062028.52610146.142033.41510159.212036.53910195.152034.70210200.912036.035
#Mann= 3 , 0 , 0
9799.078  0.0646       09799.078  0.0646       010200.91  0.0646       0
#XS Ineff= 2 , 0
       0                               0
Bank Sta=9799.078,10200.91
Exp/Cntr=0.3,0.1

Type RM Length L Ch R = 1 ,6266.233,146.221400,146.221400,146.221400
XS GIS Cut Line= 6
705250.576915234764325.265271246705228.298846066764400.453754619
 705248.39912733 764443.65311151705242.271053535764480.029339949
705246.137216397764518.305995101705288.110353954764653.225004927
#Sta/Elev= 30
9857.4052020.9479867.5592020.5179877.9882019.4439888.418 2016.999898.8482015.723
9909.277 2015.579912.2372015.7519919.7072015.896 9951.712014.2899983.4722008.709
9994.8892007.94310005.71 2006.6110015.91 2008.5710025.962013.76310035.962018.419
10046.052022.33810056.172025.62510066.422027.20110076.752029.12110097.412032.016
10107.742033.31910112.582034.317 10118.22035.22810129.712036.78710149.922037.618
10160.492037.50510171.062038.07210181.642038.08410192.212039.678 10200.92039.146
#Mann= 3 , 0 , 0
9857.405    0.04       09857.405    0.04       0 10200.9    0.04       0
#XS Ineff= 2 , 0
       0                               0
Bank Sta=9857.405,10200.9
Exp/Cntr=0.3,0.1

Type RM Length L Ch R = 1 ,6120.012,146.221300,146.221300,146.221300
XS GIS Cut Line= 6
705088.545396623764193.922112302705103.295427337764265.778636635
705115.445264307764363.478823962705129.374506989764405.460813401
 705135.80929052764435.057110036705155.360003337764589.264841886
#Sta/Elev= 30
9799.0692035.5829820.5872033.1699830.7952032.3039841.0042030.6219851.2122029.503
9881.7172026.6079891.794 2025.429901.8712024.7989911.9482023.3199922.0252022.814
9932.1022021.4429962.3332016.6559972.448 2012.819982.7772008.1859988.6722006.434
9993.2852005.45310004.052006.29610024.952007.33210035.182009.03310045.412012.531
10055.482015.09810065.552016.02110095.752019.90710105.822020.92210115.892027.455
10125.962027.89410136.032030.31910156.172029.06910176.392031.28610200.932031.826
#Mann= 3 , 0 , 0
9799.069    0.04       09799.069    0.04       010200.93    0.04       0
#XS Ineff= 2 , 0
       0                               0
Bank Sta=9799.069,10200.93
Exp/Cntr=0.3,0.1

Type RM Length L Ch R = 1 ,5973.791,165.501100,165.501100,165.501100
XS GIS Cut Line= 6
705048.034593609764223.561627451705061.217465201764312.157505579
705058.205973311764378.031284228705004.702587871 764444.27921652
704996.774534221764467.482440514 705025.66071918764598.477934021
#Sta/Elev= 30
9799.1472035.4359810.7842033.0829841.3062027.7879851.4352025.6229861.489 2023.06
9871.5432021.0599881.5962018.6769891.6352017.2539901.6362016.4939911.6372016.434
9921.6382015.6199931.686 2014.479951.8142013.2149962.1992012.2499973.2192010.701
9985.5732007.1579999.4722005.05510012.392005.612 10025.72010.29110028.67 2010.95
10041.022013.15110063.652016.22210103.992018.90310123.282020.588   101352020.948
10145.382022.04610166.132022.511 10176.52023.42510197.252023.95910200.862024.307
#Mann= 3 , 0 , 0
9799.147    0.04       09799.147    0.04       010200.86    0.04       0
#XS Ineff= 2 , 0
       0                               0
Bank Sta=9799.147,10200.86
Exp/Cntr=0.3,0.1

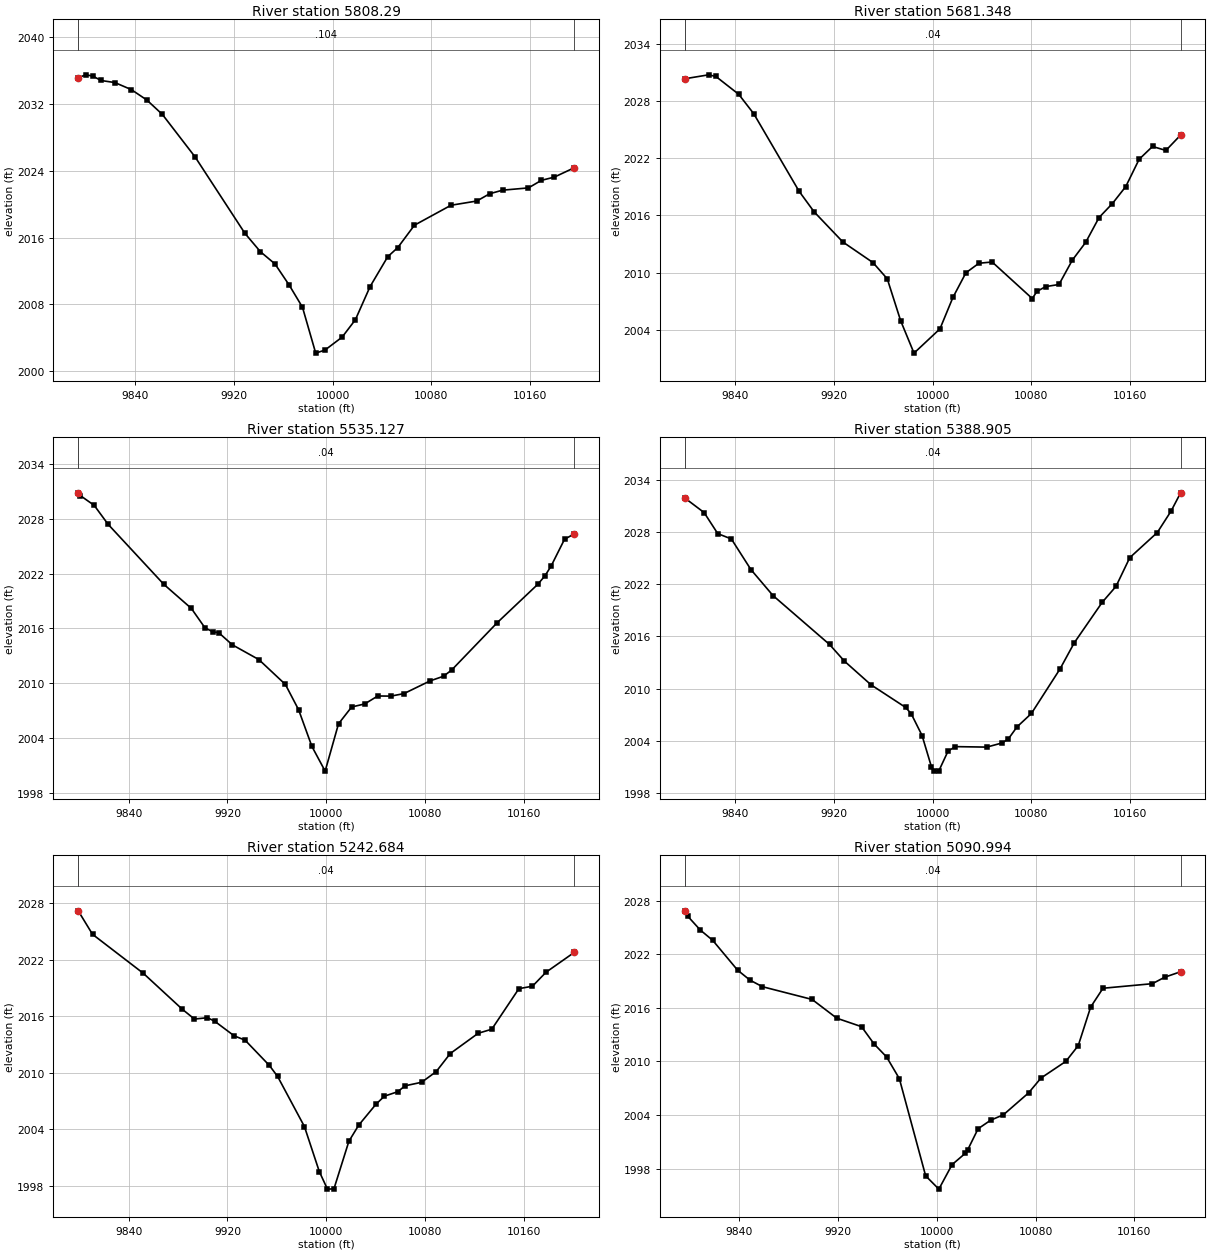
Type RM Length L Ch R = 1 , 5808.29,126.941700,126.941700,126.941700
XS GIS Cut Line= 6
704778.355811842764319.723927624704860.090629794764418.784910897
704894.587464075764442.048593243704947.292323263764462.296682815
704965.054071634764477.994360527705013.981144434764620.387514492
#Sta/Elev= 30
9793.8532035.1429800.2292035.4659805.6872035.3149812.3132034.7889823.499 2034.54
9836.7962033.7039849.4022032.4569862.0082030.7319888.5392025.6419928.8692016.506
9941.4432014.3059953.2332012.8449964.8172010.2999975.5272007.6589986.2362002.171
9993.7532002.53810007.642004.08510018.382006.16710030.292010.133 10044.62013.708
10052.752014.80210066.222017.47510095.822019.86110116.742020.368 10127.22021.242
10137.662021.66610158.592021.93910169.052022.84210179.512023.227 10195.62024.342
#Mann= 3 , 0 , 0
9793.853   0.104       09793.853   0.104       0 10195.6   0.104       0
#XS Ineff= 2 , 0
       0                               0
Bank Sta=9793.853,10195.6
Exp/Cntr=0.3,0.1

Type RM Length L Ch R = 1 ,5681.348,146.221400,146.221400,146.221400
XS GIS Cut Line= 6
704740.487432378 764359.12858217704814.067598216764464.121230195
704832.077404287764494.019870907704840.345160531 764513.54545176
704858.403389979764568.626423285704919.672467733764716.030302471
#Sta/Elev= 30
 9799.062030.3259818.441 2030.749824.3472030.5699842.8632028.6989855.0742026.657
9891.7082018.5519903.9192016.3869927.2692013.2189951.6432011.0639963.2372009.361
9974.0962004.9639984.9062001.57210005.932004.11510016.462007.41410026.992009.994
10037.522010.99310048.242011.12310080.732007.29410084.582008.04310091.562008.542
10102.392008.76610113.222011.32110124.052013.18510134.882015.78610145.712017.253
10156.542019.03310167.372021.893 10178.22023.23210189.032022.81510200.972024.427
#Mann= 3 , 0 , 0
 9799.06    0.04       0 9799.06    0.04       010200.97    0.04       0
#XS Ineff= 2 , 0
       0                10037.07       0
Bank Sta=9799.06,10200.97
Exp/Cntr=0.3,0.1

Type RM Length L Ch R = 1 ,5535.127,146.221400,146.221400,146.221400
XS GIS Cut Line= 6
704635.388195331764403.485315758704674.698190283764479.188511957
704692.908012645764518.029482182704723.983129525764596.550510862
704748.649517844764666.443601938704794.429001458764772.143893429
#Sta/Elev= 30
9799.022 2030.849800.7292030.5399811.9962029.4669823.2642027.3919868.3362020.834
9890.7412018.1869901.7862016.0589908.5912015.604 9912.832015.5459923.8752014.211
 9945.452012.5889966.9332009.8699977.6752007.0929988.4172003.0879999.1622000.382
10009.992005.56210020.63  2007.410031.232007.73710041.842008.60710052.442008.591
10063.052008.86710084.26 2010.2610095.112010.76710101.772011.456 10138.72016.638
 10171.42020.81410177.252021.74310182.292022.82110193.19 2025.7610200.982026.338
#Mann= 3 , 0 , 0
9799.022    0.04       09799.022    0.04       010200.98    0.04       0
#XS Ineff= 2 , 0
       0                               0
Bank Sta=9799.022,10200.98
Exp/Cntr=0.3,0.1

Type RM Length L Ch R = 1 ,5388.905,146.221300,146.221300,146.221300
XS GIS Cut Line= 6
704502.484625919764490.705243393704554.292860174764592.345947668
704583.697405599764635.607519096704647.116156689764711.956920954
704676.559823366764762.098495045704711.088774351 764831.93411161
#Sta/Elev= 30
 9799.072031.9519814.841 2030.269825.8742027.8389836.9062027.2269852.7232023.706
9870.5982020.7169916.4252015.0839928.5172013.1619950.0532010.4389978.0772007.837
9982.5632007.123 9991.442004.598    99992001.006   100012000.55910004.922000.501
10012.492002.806 10018.42003.32210043.842003.26610056.252003.74210061.322004.205
10068.422005.59910080.022007.13510103.212012.26110114.812015.28410137.432019.938
10148.59 2021.7710159.742025.07310182.052027.96810193.212030.43510200.942032.536
#Mann= 3 , 0 , 0
 9799.07    0.04       0 9799.07    0.04       010200.94    0.04       0
#XS Ineff= 2 , 0
       0                               0
Bank Sta=9799.07,10200.94
Exp/Cntr=0.3,0.1

Type RM Length L Ch R = 1 ,5242.684,151.689500,151.689500,151.689500
XS GIS Cut Line= 6
 704396.63742577764543.740717885704437.267192347764677.957105857
704456.417505622764703.011691656704497.768546427764731.735898343
704521.702530551764758.751295109704586.861960226764885.748942688
#Sta/Elev= 30
9799.0972027.161 9810.692024.6739851.8732020.5389883.451 2016.739893.2852015.692
9903.8262015.8379909.6572015.4659925.4612013.9159934.2722013.4619954.0022010.775
9960.6532009.6119982.3712004.3069994.4231999.538   100011997.67510006.281997.702
 10018.42002.74710026.392004.45910040.312006.66510047.172007.52510057.912007.992
10063.962008.62310077.292008.99510089.112010.12310100.532012.04210123.172014.189
10134.162014.61710156.132018.91510167.122019.17310178.112020.654 10200.92022.749
#Mann= 3 , 0 , 0
9799.097    0.04       09799.097    0.04       0 10200.9    0.04       0
#XS Ineff= 2 , 0
       0                               0
Bank Sta=9799.097,10200.9
Exp/Cntr=0.3,0.1

Type RM Length L Ch R = 1 ,5090.994,143.677100,143.677100,143.677100
XS GIS Cut Line= 6
704368.344482928764552.447930763704380.816615858764692.371054895
704376.053668455764720.815122816704354.929421131  764777.0649527
704345.595887279764817.139831949704338.514109373764947.888510706
#Sta/Elev= 30
9795.7172026.8799798.2872026.2619808.3592024.728 9818.432023.5729838.5732020.233
9848.6452019.1119858.7172018.3769898.9462016.9489918.9532014.8459938.9952013.897
9949.1342011.9629959.2742010.5069969.6272008.0749990.9281997.18110001.641995.692
10012.341998.43710023.051999.70410025.062000.11310033.412002.45510043.672003.422
10053.942004.02410074.312006.47510084.372008.14110104.492010.00610114.552011.773
 10124.62016.091 10134.62018.203 10174.62018.714 10184.6 2019.4410197.492020.053
#Mann= 3 , 0 , 0
9795.717    0.04       09795.717    0.04       010197.49    0.04       0
#XS Ineff= 2 , 0
       0                               0
Bank Sta=9795.717,10197.49
Exp/Cntr=0.3,0.1

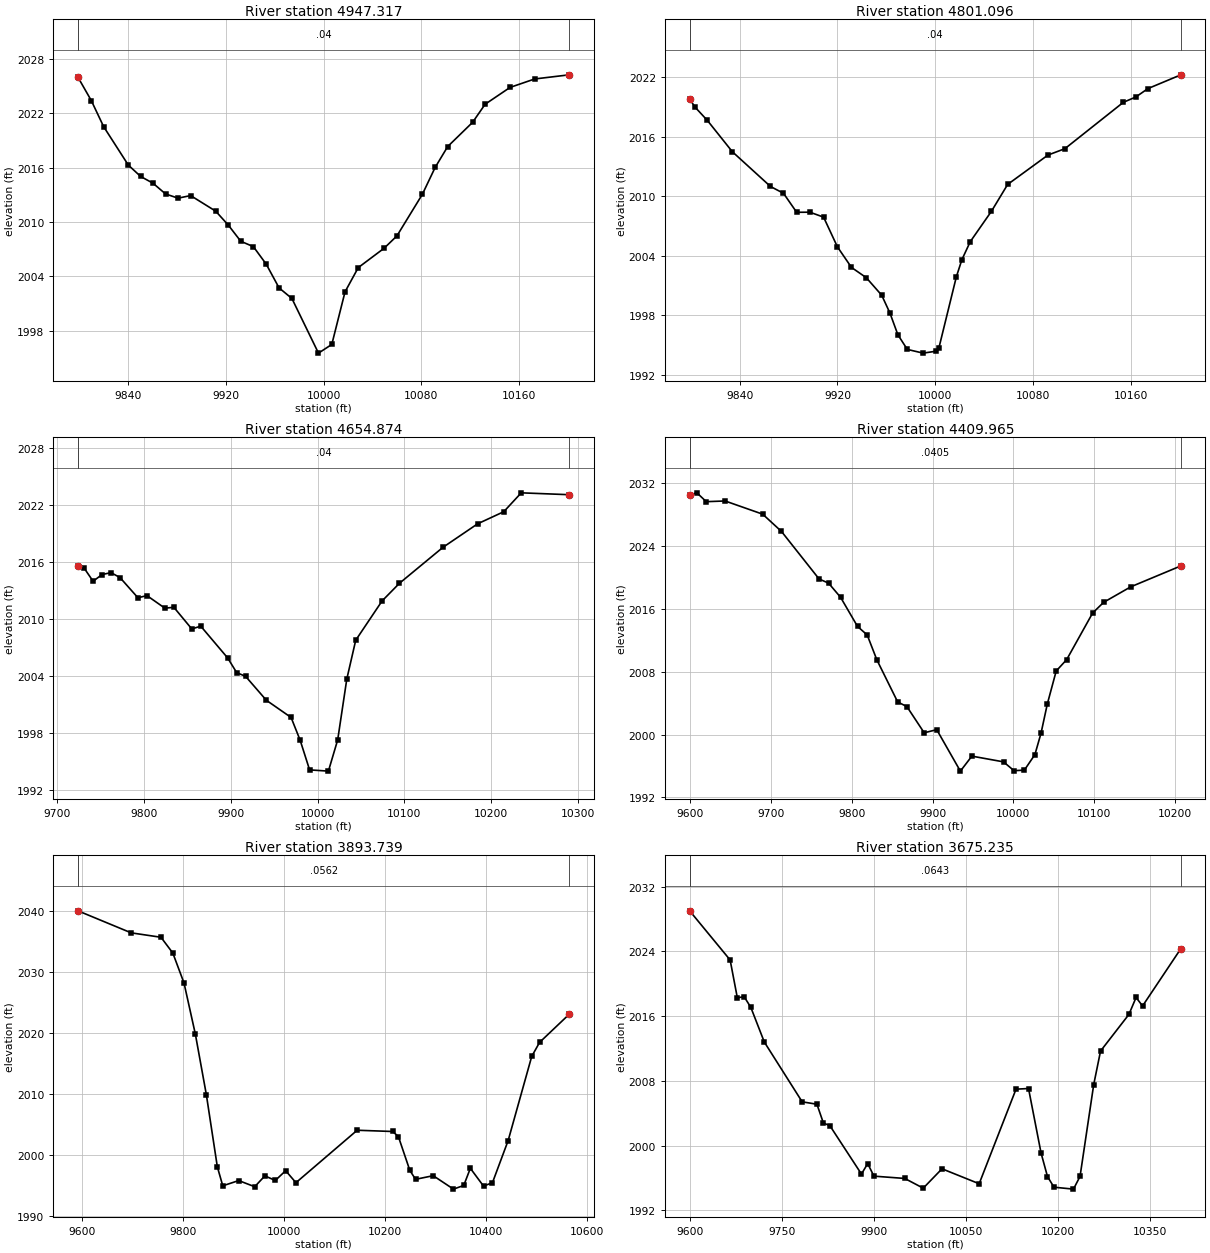
Type RM Length L Ch R = 1 ,4947.317,146.221400,146.221400,146.221400
XS GIS Cut Line= 6
704271.161745408764534.209009332704262.770396625764594.224524431
704245.006304177764672.253096079704209.750877598764763.678473367
704193.412246388764819.451397156704176.725795613764923.062771808
#Sta/Elev= 30
9799.0612025.9769809.9572023.4029820.0542020.5279840.2492016.2859850.3462015.029
9860.4562014.2839870.7122013.0999880.9682012.6349891.2242012.9219911.735  2011.2
9921.9912009.6739932.247 2007.889942.5712007.2849953.0732005.3529963.5762002.735
9974.0792001.5669995.8221995.53610006.721996.49410017.55  2002.310028.372004.973
10049.572007.11510059.992008.46910080.832013.06410091.25 2016.0210101.552018.331
10121.952021.00810132.142022.99610152.542024.85410172.692025.78710200.932026.244
#Mann= 3 , 0 , 0
9799.061    0.04       09799.061    0.04       010200.93    0.04       0
#XS Ineff= 2 , 0
       0                               0
Bank Sta=9799.061,10200.93
Exp/Cntr=0.3,0.1

Type RM Length L Ch R = 1 ,4801.096,146.221400,146.221400,146.221400
XS GIS Cut Line= 6
704187.066937955764490.789951002704170.327949006764559.190434829
704145.374707092764612.795017316704044.822447959764723.533051397
704030.423179104764769.423038466704024.861999963764841.897587209
#Sta/Elev= 30
9799.108  2019.89803.3962018.9949813.5822017.6399834.0022014.4869865.2372010.978
9875.8632010.2939886.6442008.3779897.4252008.388 9908.662007.8899919.983 2004.89
9931.4782002.8199943.5772001.7879956.1972000.0189962.9021998.2289969.4461996.027
9977.1311994.5569990.0941994.18110000.671994.37510002.881994.65610017.272001.883
10021.792003.60310028.622005.41410045.992008.48610059.222011.18710092.172014.146
10106.042014.78910153.872019.46610163.942019.99210173.982020.84810200.882022.234
#Mann= 3 , 0 , 0
9799.108    0.04       09799.108    0.04       010200.88    0.04       0
#XS Ineff= 2 , 0
       0                               0
Bank Sta=9799.108,10200.88
Exp/Cntr=0.3,0.1

Type RM Length L Ch R = 1 ,4654.874,244.909900,244.909900,244.909900
XS GIS Cut Line= 6
703900.512416047764358.177073572703956.136776791764568.076814012
703989.628604966764659.017921241703995.389166226764693.453851404
704001.064952555764807.722018122704014.962430893764909.546833996
#Sta/Elev= 30
9723.6922015.5339730.7822015.3429741.126 2013.969751.4692014.6669761.8132014.863
9772.1572014.3459792.844 2012.229803.1882012.4519823.8752011.1279834.2192011.221
9854.9062008.943 9865.252009.2359896.281 2005.899906.6252004.3519916.9692003.953
9940.8392001.4429969.3691999.6329979.8941997.2179990.7081994.118 10012.41993.987
 10023.11997.27710033.612003.67510043.892007.75610074.29 2011.8910094.322013.748
10144.382017.52110184.432020.00210214.592021.27510234.71 2023.2610289.972023.063
#Mann= 3 , 0 , 0
9723.692    0.04       09723.692    0.04       010289.97    0.04       0
#XS Ineff= 2 , 0
       0                               0
Bank Sta=9723.692,10289.97
Exp/Cntr=0.3,0.1

Type RM Length L Ch R = 1 ,4409.965,516.225400,516.225400,516.225400
XS GIS Cut Line= 6
703548.443989513764437.290887308703634.538830174764581.524186786
703698.158110637764673.675525506703745.976292749764726.259357457
703861.381501179764830.663790372703917.264459889764915.398626002
#Sta/Elev= 30
9599.0552030.5389608.0332030.7899619.6792029.6629642.9712029.7519689.555 2028.07
9712.8472025.8699759.4322019.816 9771.192019.2879786.0642017.483  9807.12013.769
9819.0692012.6849831.0472009.5139856.8362004.1519868.2772003.5589889.6842000.222
9905.233 2000.629934.5241995.3399948.7841997.2499987.9991996.51910000.981995.398
 10013.81995.46210026.891997.44610034.492000.17610042.262003.88510053.282008.095
10066.262009.54410098.43 2015.4810112.062016.84110145.572018.81110207.752021.479
#Mann= 3 , 0 , 0
9599.055  0.0405       09599.055  0.0405       010207.75  0.0405       0
#XS Ineff= 2 , 0
       0                               0
Bank Sta=9599.055,10207.75
Exp/Cntr=0.3,0.1

Type RM Length L Ch R = 1 ,3893.739,218.504200,218.504200,218.504200
XS GIS Cut Line= 6
703030.252009749764849.332973227703225.251464099764975.642113566
703521.439313948765060.308492139703635.990956932 765117.19401966
703699.386882991765155.318651572703874.906145066 765302.71555534
#Sta/Elev= 30
9591.882 2040.119697.2932036.498 9756.242035.7769779.7392033.1899801.9252028.267
9824.4362019.8679846.1722009.9529867.8981998.139 9878.651995.0219910.266 1995.88
 9941.921994.8729962.0751996.654 9982.691995.89410003.231997.50210023.571995.532
10144.872004.13210215.132003.92710226.472003.10110249.151997.55210260.491996.085
10295.46 1996.6810335.591994.47710355.981995.08110369.031997.89110395.151994.974
10412.841995.53610443.94 2002.4510490.592016.23710506.142018.53810564.792023.147
#Mann= 3 , 0 , 0
9591.882  0.0562       09591.882  0.0562       010564.79  0.0562       0
#XS Ineff= 2 , 0
       0                10173.46       0
Bank Sta=9591.882,10564.79
Exp/Cntr=0.3,0.1

Type RM Length L Ch R = 1 ,3675.235,244.909900,244.909900,244.909900
XS GIS Cut Line= 6
703086.420949824765126.935777868703221.230623146765193.943581863
703359.125685426765235.348840441703546.014600229765222.780487363
703637.933681572765234.845979257703834.495921281765341.837547269
#Sta/Elev= 30
9599.1212029.0049665.1982022.931 9676.982018.252 9687.972018.4129698.9612017.081
9720.9432012.8069782.7682005.4169806.842 2005.129817.456 2002.799827.8452002.487
 9879.481996.4989889.7181997.7899899.8771996.2399950.1651995.9559980.3461994.755
10010.981997.14710071.63  1995.310131.772006.97910152.192007.06110172.621999.106
10183.111996.19310193.721994.87410225.541994.63610236.291996.21510258.582007.549
10269.722011.68710315.992016.20710327.722018.303 10338.32017.254 10400.82024.333
#Mann= 3 , 0 , 0
9599.121  0.0643       09599.121  0.0643       0 10400.8  0.0643       0
#XS Ineff= 2 , 0
       0                10142.23       0
Bank Sta=9599.121,10400.8
Exp/Cntr=0.3,0.1

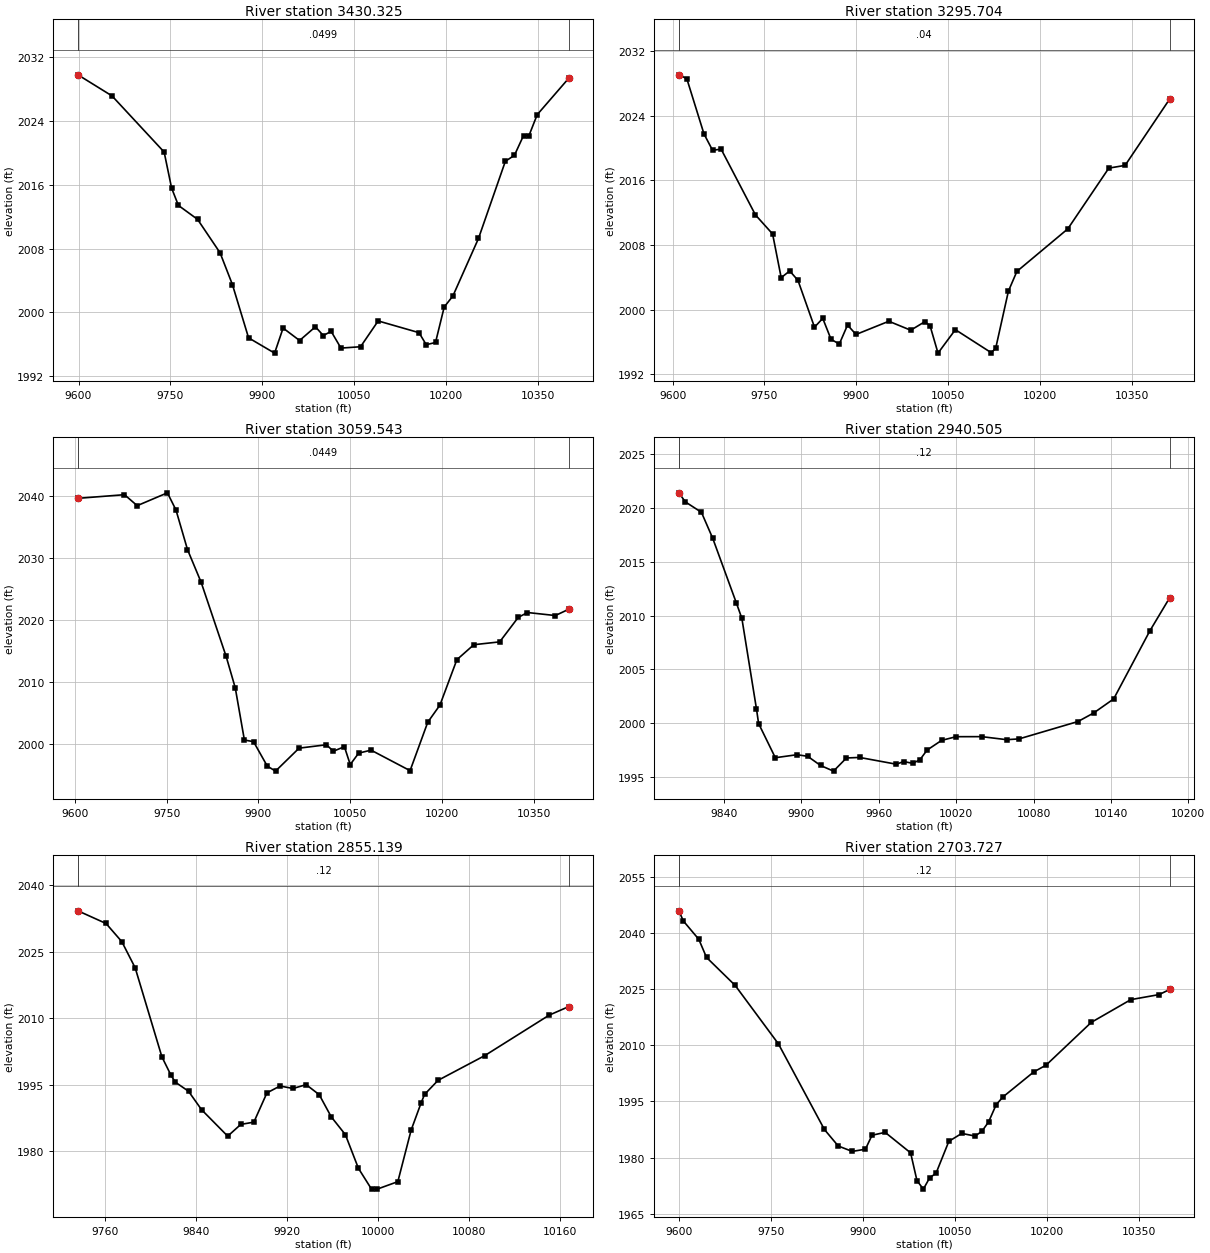
Type RM Length L Ch R = 1 ,3430.325,134.621200,134.621200,134.621200
XS GIS Cut Line= 6
703019.257989815  765151.5668273 703179.87185824765262.803866001
703249.270406717765318.428236087703295.419442883765366.381464616
  703443.1199594765542.906253634703603.214889202 765694.83558319
#Sta/Elev= 30
 9599.062029.7889654.7012027.144 9739.852020.1059752.014 2015.599763.1622013.411
9794.4322011.6649831.1642007.4769851.3772003.4869877.7771996.8059920.2921994.889
9934.1711998.0329961.1041996.4729986.9471998.1919999.8571997.09610012.671997.618
10028.68 1995.52 10060.7 1995.6910089.481998.92610156.211997.455   101681995.942
10183.171996.22410197.362000.67410211.542002.05510253.352009.26810297.252018.945
 10312.12019.69810326.952022.17510335.75 2022.1510349.282024.79410400.962029.374
#Mann= 3 , 0 , 0
 9599.06  0.0499       0 9599.06  0.0499       010400.96  0.0499       0
#XS Ineff= 2 , 0
       0                               0
Bank Sta=9599.06,10400.96
Exp/Cntr=0.3,0.1

Type RM Length L Ch R = 1 ,3295.704,236.160500,236.160500,236.160500
XS GIS Cut Line= 6
702955.407633314 765205.74553297703080.789843869765333.376371389
703244.590546536765514.039914482703309.997004375765582.696292933
703404.278135043765673.071120459703519.769074485765774.564940637
#Sta/Elev= 30
 9610.112029.0819623.0832028.6099651.1192021.7699665.1372019.7389679.1552019.874
9735.2282011.7299763.2642009.3669777.2822003.9559791.2152004.7919804.7092003.617
9831.6971997.8229845.1911998.9139858.6851996.3269872.179 1995.739885.6731998.084
 9899.55 1996.929953.1431998.5569988.9121997.44610012.091998.50810020.651997.955
10033.481994.60810061.841997.51510120.471994.66110127.711995.207 10148.52002.289
10162.35 2004.7310245.462009.99610312.532017.52310339.152017.86510412.062026.095
#Mann= 3 , 0 , 0
 9610.11    0.04       0 9610.11    0.04       010412.06    0.04       0
#XS Ineff= 2 , 0
       0                               0
Bank Sta=9610.11,10412.06
Exp/Cntr=0.3,0.1

Type RM Length L Ch R = 1 ,3059.543,119.038000,119.038000,119.038000
XS GIS Cut Line= 6
 702777.18308009 765360.76376416702902.565290645 765488.39460258
703066.365993311765669.058145672703131.772451151765737.714524123
703226.053581819765828.089351649 703341.54452126765929.583171827
#Sta/Elev= 30
9605.1082039.6599681.1372040.248 9701.882038.4739751.2282040.5489765.2462037.772
9784.0222031.384 9806.432026.0679847.2232014.1039862.1172009.0239877.0112000.601
9891.9042000.3429914.3821996.3939927.8761995.5779966.372 1999.2910011.031999.837
10022.391998.792 10040.4 1999.5310049.911996.64110063.721998.484 10083.91998.969
10147.691995.65310176.592003.48510196.442006.24410224.152013.58510251.852016.005
10294.082016.46410324.382020.41910339.522021.20710385.042020.71810407.062021.743
#Mann= 3 , 0 , 0
9605.108  0.0449       09605.108  0.0449       010407.06  0.0449       0
#XS Ineff= 2 , 0
       0                               0
Bank Sta=9605.108,10407.06
Exp/Cntr=0.3,0.1

Type RM Length L Ch R = 1 ,2940.505,85.366500,85.366500,85.366500
XS GIS Cut Line= 6
702889.099055737765570.252199829702903.086081445765609.294465408
702938.334397912765651.999156564702943.757215858765722.495789573
702993.918281645765748.254174694703106.446812153765855.708930582
#Sta/Elev= 30
9804.926 2021.429809.9692020.5789822.422 2019.619831.2142017.1869849.4052011.218
9853.7962009.7459865.1142001.3299866.7621999.9729879.7291996.7919896.5321997.071
9904.7831996.926 9914.82 1996.079924.8571995.5459934.8941996.7689945.0591996.818
9973.6341996.1879979.2341996.4379986.2041996.2719991.8231996.594 9997.431997.502
 10008.71998.40510019.971998.74710039.791998.75110059.171998.46810068.751998.542
10114.482000.15810126.672000.95510142.142002.25910170.112008.56810185.622011.676
#Mann= 3 , 0 , 0
9804.926    0.12       09804.926    0.12       010185.62    0.12       0
#XS Ineff= 2 , 0
       09963.676        10050.39       0
Bank Sta=9804.926,10185.62
Exp/Cntr=0.3,0.1

Type RM Length L Ch R = 1 ,2855.139,151.411300,151.411300,151.411300
XS GIS Cut Line= 6
702822.032369478765582.127924912702871.240791337765661.994668356
702954.328794284  765808.1912777 702968.09522305 765831.60810696
703005.474696883765890.386844252703049.390134089765948.886007787
#Sta/Elev= 30
9736.1862034.2229760.9082031.3639774.7972027.2559786.5432021.3499810.0342001.262
9818.098 1997.08 9821.781995.5619833.4521993.4929844.9551989.3259867.9591983.352
9879.4611986.0059890.9631986.5179902.4661993.1249913.9681994.674 9925.471994.116
9936.9721994.9859948.4741992.7179959.035 1987.729971.4791983.6999982.9811976.086
9994.483  1971.4 9999.491971.39610017.651973.08510029.341984.71110038.181990.897
10041.191992.78410053.041995.95410094.092001.52910150.762010.66510168.122012.609
#Mann= 3 , 0 , 0
9736.186    0.12       09736.186    0.12       010168.12    0.12       0
#XS Ineff= 2 , 0
       09932.725                       0
Bank Sta=9736.186,10168.12
Exp/Cntr=0.3,0.1

Type RM Length L Ch R = 1 ,2703.727,151.411400,151.411400,151.411400
XS GIS Cut Line= 6
702619.665216908 765509.18881827702766.767260407765727.952406069
702832.432228057765919.837303883702867.334815825765985.611127472
702941.797873634766063.162437039703070.042136879766144.813398517
#Sta/Elev= 30
9599.062  2045.99606.3912043.1899631.6152038.2959644.2272033.4569691.0152025.982
9761.7232010.3529836.7961987.4959859.4211983.0849882.2561981.6429903.8041982.233
9914.5491985.9579935.9681986.7359977.6081981.2549988.0181973.8319998.4281971.569
10008.791974.60710019.151975.81610040.041984.32810061.151986.45110082.951985.741
10093.951986.99910104.96 1989.5110117.37 1994.1210128.391996.18210178.712002.866
10198.962004.69410272.72 2016.11 10337.3 2022.1810383.512023.52710400.882024.901
#Mann= 3 , 0 , 0
9599.062    0.12       09599.062    0.12       010400.88    0.12       0
#XS Ineff= 2 , 0
       09943.139                       0
Bank Sta=9599.062,10400.88
Exp/Cntr=0.3,0.1