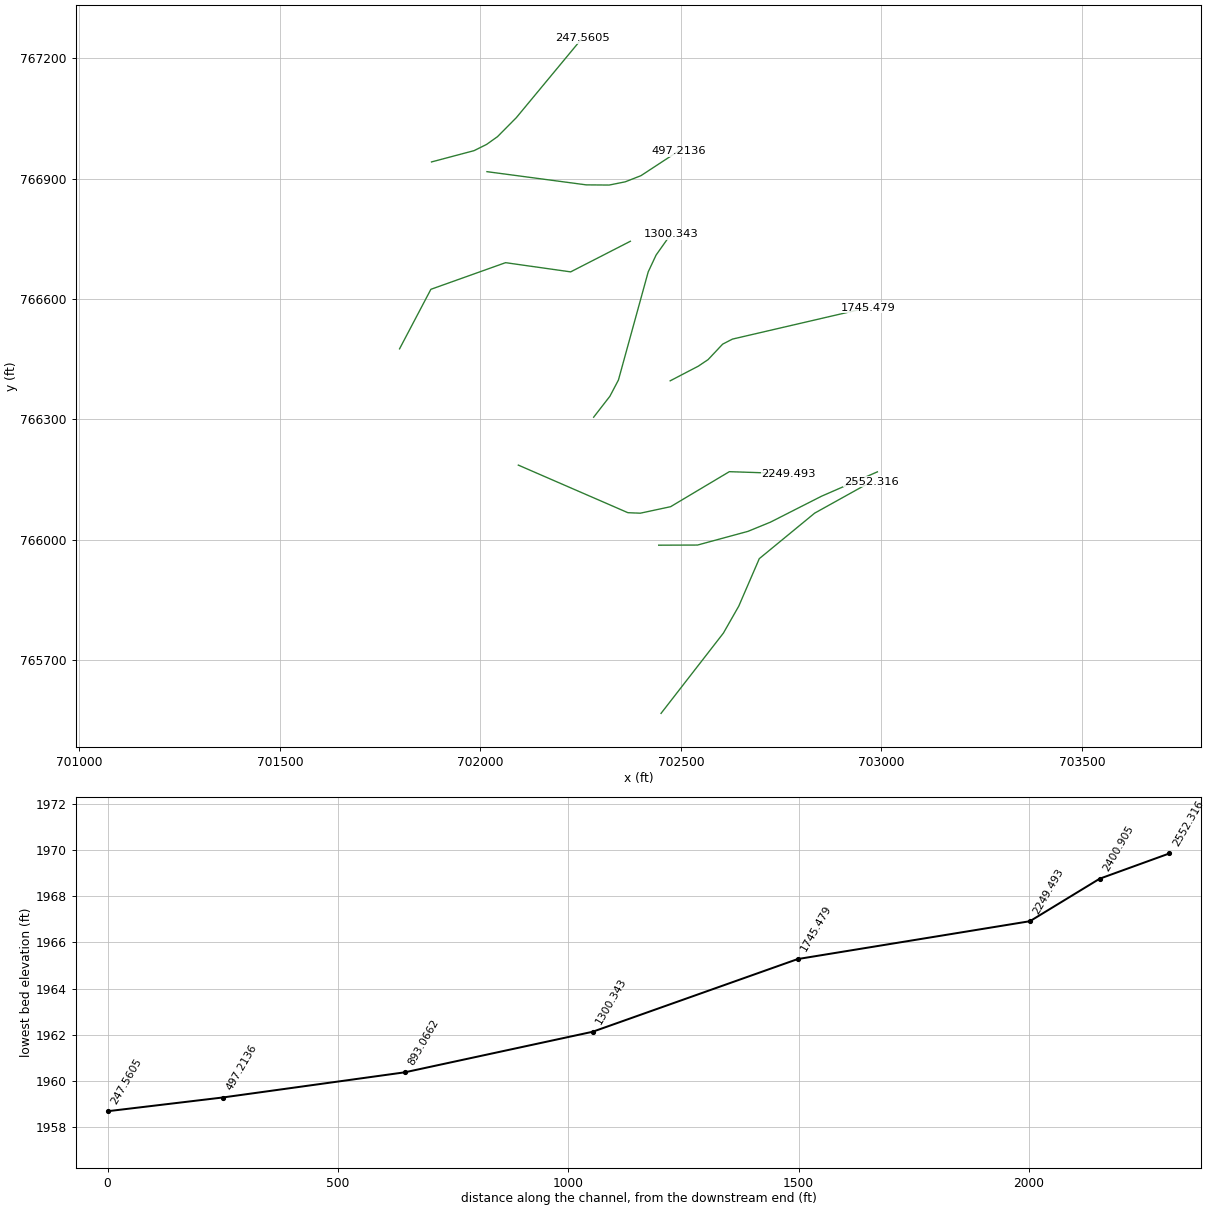
HEC-RAS study 14448_ras.prj: 14448

--- 14448_ras.g01 (geometry) --- (continued)

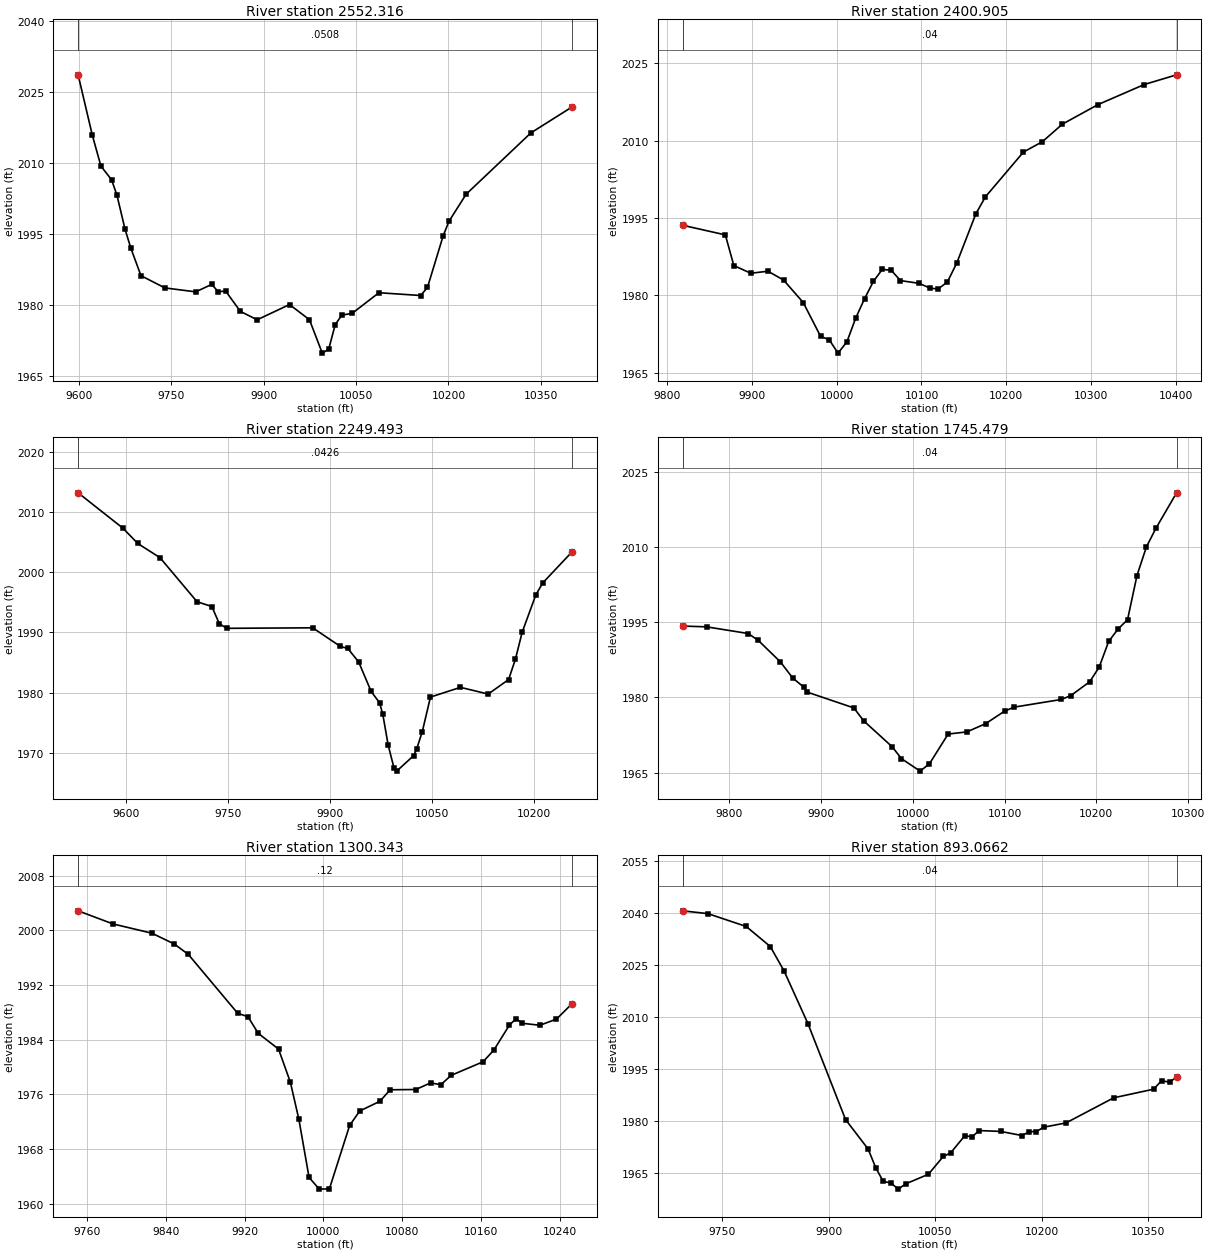
Type RM Length L Ch R = 1 ,2552.316,151.411400,151.411400,151.411400
XS GIS Cut Line= 6
702450.349802136765566.526976274702605.825326919765766.692915817
702644.190723132765834.012358957 702695.36078088765952.358726344
702833.448018153766065.849351305702974.681158877766144.305247676
#Sta/Elev= 30
 9599.072028.635 9622.01 2015.949636.0712009.3589653.3272006.4719662.0612003.232
9675.0571996.0939684.6441992.0219701.0471986.2179739.8881983.6289789.9331982.797
9815.8291984.3679826.424 1982.849838.5411982.9499862.4281978.6689889.6421976.896
9942.1461980.117 9974.491976.9139995.3241969.85410005.771970.67710016.271975.862
10027.011977.88610043.741978.24910087.261982.61210154.941982.02410166.031983.722
10191.541994.64810201.071997.72810228.792003.419 10333.82016.36210400.882021.869
#Mann= 3 , 0 , 0
 9599.07  0.0508       0 9599.07  0.0508       010400.88  0.0508       0
#XS Ineff= 2 , 0
       09941.319                       0
Bank Sta=9599.07,10400.88
Exp/Cntr=0.3,0.1

Type RM Length L Ch R = 1 ,2400.905,151.411300,151.411300,151.411300
XS GIS Cut Line= 6
702444.468454808 765985.90967603  702541.3511886765986.269666061
702667.238965929766020.434775114 702723.20100224 766043.36771594
  702850.4559443766107.984568819702989.910057157766168.821820408
#Sta/Elev= 30
9818.0951993.5689868.6271991.6979878.6271985.7499898.6271984.255 9918.861984.648
9937.295 1982.949960.5071978.5749980.9871972.0169991.2281971.34210001.54 1968.76
10011.971970.92810022.391975.54610032.821979.30110043.241982.65810053.831985.017
10064.471984.81310075.171982.834 10097.11982.301 10109.71981.40110119.331981.176
10130.541982.53610141.76 1986.2910164.19 1995.7910175.411999.07110220.272007.759
 10242.72009.78310266.362013.19110308.322016.97610362.88 2020.8710400.962022.747
#Mann= 3 , 0 , 0
9818.095    0.04       09818.095    0.04       010400.96    0.04       0
#XS Ineff= 2 , 0
       0                               0
Bank Sta=9818.095,10400.96
Exp/Cntr=0.3,0.1

Type RM Length L Ch R = 1 ,2249.493,504.014100,504.014100,504.014100
XS GIS Cut Line= 6
702094.494354874766185.570041686702367.740684867766066.941060841
702398.500740319766065.661473766702474.209640086766081.895351648
 702620.67336908766169.231959686702768.138868809766164.320930168
#Sta/Elev= 30
9529.1322013.2219595.0942007.3389616.8982004.7949649.6032002.4359704.1121995.107
9725.9151994.3069736.8171991.4719747.7191990.6799874.3261990.7649915.1291987.662
9925.968 1987.339942.0291985.084 9960.331980.1849972.8751978.2689977.5561976.346
 9985.421971.2349994.1181967.4029997.9651966.92110023.061969.51510027.211970.543
10035.671973.50710047.651979.24310091.841980.85910132.591979.73910162.61 1982.15
10172.631985.51710182.651990.044 10202.71996.22910212.741998.21610256.212003.425
#Mann= 3 , 0 , 0
9529.132  0.0426       09529.132  0.0426       010256.21  0.0426       0
#XS Ineff= 2 , 0
       0                               0
Bank Sta=9529.132,10256.21
Exp/Cntr=0.3,0.1

Type RM Length L Ch R = 1 ,1745.479,445.136300,445.136300,445.136300
XS GIS Cut Line= 6
702473.136483282766395.747734219702543.360175639766432.347434819
702567.762639344766448.707188845 702603.97740075766487.229745388
702628.395377725766499.780764818702966.890188217766578.365180597
#Sta/Elev= 30
9749.2181994.2679775.6231994.1029820.8051992.769 9831.83 1991.389855.9091987.089
9869.217 1983.899881.5771982.0189884.8361981.0819935.8751977.9069946.5571975.326
9977.5291970.1589987.6841967.777   100081965.28310018.171966.741 10038.51972.688
10058.941973.12110079.531974.78110100.121977.27910110.411978.06610161.871979.599
10172.171980.37310192.751983.13710203.051986.05610213.341991.17910223.631993.674
10233.931995.53210244.222004.36110254.51 2010.0910264.812013.77910287.342020.878
#Mann= 3 , 0 , 0
9749.218    0.04       09749.218    0.04       010287.34    0.04       0
#XS Ineff= 2 , 0
       0                               0
Bank Sta=9749.218,10287.34
Exp/Cntr=0.3,0.1

Type RM Length L Ch R = 1 ,1300.343,407.276800,407.276800,407.276800
XS GIS Cut Line= 6
702282.302341415766305.053844708702322.825621991766357.316710088
702344.086316335766397.728658612702418.344118447766667.366219181
702437.946993301766709.262410032702474.755683653766761.276174649
#Sta/Elev= 30
 9750.822002.8439786.3062000.9229825.7111999.574 9848.311998.0059862.6921996.477
9912.9061987.8589923.3541987.3549933.7561984.9289954.4131982.6189966.426 1977.77
9975.0711972.3379985.3991963.8529995.7281962.13710006.051962.17310026.651971.465
10036.911973.56810057.441974.98910067.711976.66810093.891976.70910108.791977.675
10119.251977.409 10129.71978.77510162.11 1980.7610173.15 1982.4810188.891986.125
10195.771987.08710201.711986.39710219.881986.10410236.73 1987.0110252.661989.272
#Mann= 3 , 0 , 0
 9750.82    0.12       0 9750.82    0.12       010252.66    0.12       0
#XS Ineff= 2 , 0
       0                               0
Bank Sta=9750.82,10252.66
Exp/Cntr=0.3,0.1

Type RM Length L Ch R = 1 ,893.0662,395.852600,395.852600,395.852600
XS GIS Cut Line= 5
701798.328239441766475.510124728701876.453239441766623.947624728
702062.651156098766690.353874743          702225766667.428157941
702373.849072814766743.739291415
#Sta/Elev= 30
9693.7652040.6369729.5612039.8289783.5922036.1269817.4942030.3479836.9152023.318
 9870.582008.1249923.6651980.4479955.5161971.9369966.1331966.607 9976.751962.602
9987.3671962.1889997.9841960.384 10008.61961.91810040.451964.66310061.561969.829
10071.661970.79310091.861975.79610101.961975.45610112.06 1977.2710142.361977.025
10172.66 1975.8310182.751976.96710192.85 1976.9710202.951978.24210234.391979.466
10301.811986.718   103581989.20310369.241991.63410380.481991.24610390.421992.665
#Mann= 3 , 0 , 0
9693.765    0.04       09693.765    0.04       010390.42    0.04       0
#XS Ineff= 2 , 0
       0                               0
Bank Sta=9693.765,10390.42
Exp/Cntr=0.3,0.1

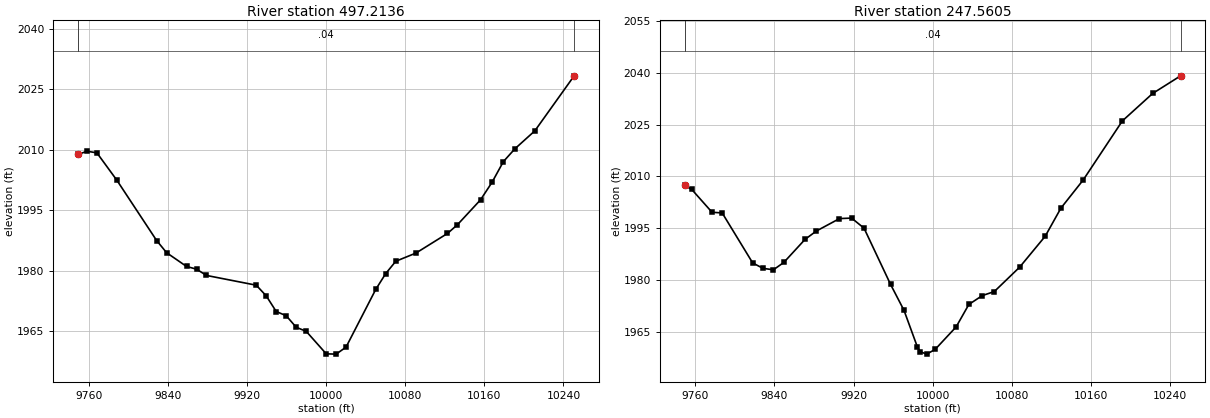
Type RM Length L Ch R = 1 ,497.2136,249.653100,249.653100,249.653100
XS GIS Cut Line= 6
702016.256811611766917.293790572702264.034334808766884.357447493
 702321.18415811766883.907284402702361.323992247766892.032331427
702400.260764076766907.298659329702493.661767413766968.463429437
#Sta/Elev= 30
9749.0222008.8039757.8362009.5999767.9162009.2039788.0762002.4299828.3971987.449
9838.4771984.4399858.637 1981.039868.717 1980.369878.7971978.8039929.1981976.382
9939.2781973.7339949.3581969.8629959.4611968.8169969.5911965.951 9979.721964.947
 9999.971959.36510009.991959.29310020.011961.02610050.061975.33410060.141979.259
10070.351982.32210090.75 1984.3510122.631989.21310132.73 1991.3810156.081997.549
10167.662001.86610179.232007.033 10190.82010.18710211.062014.66110250.822028.296
#Mann= 3 , 0 , 0
9749.022    0.04       09749.022    0.04       010250.82    0.04       0
#XS Ineff= 2 , 0
       0                               0
Bank Sta=9749.022,10250.82
Exp/Cntr=0.3,0.1

Type RM Length L Ch R = 1 ,247.5605,0.000000,0.000000,0.000000
XS GIS Cut Line= 6
701877.989064793766941.539168203701984.259196196766969.743905521
702015.371297102766985.248878723702042.503662131767004.540803307
702089.493018034767051.928856037 702253.45522899767249.750553395
#Sta/Elev= 30
9749.1152007.4049756.302 2006.249776.8051999.6589787.0561999.4749817.9311985.033
9828.4361983.4569838.9411983.0599849.4451985.1759870.9561991.8459882.345 1994.24
9905.7481997.8319918.0181997.9849930.6181995.0699957.434 1978.859971.0751971.333
9984.6291960.7469987.3661959.4139994.0211958.69910002.561960.05510023.831966.567
10036.691973.046 10050.31975.604 10062.41976.75510088.111983.81710113.951992.736
10129.86 2000.8610152.39 2008.9810192.052026.042 10222.72033.96810250.992039.058
#Mann= 3 , 0 , 0
9749.115    0.04       09749.115    0.04       010250.99    0.04       0
#XS Ineff= 2 , 0
       0                               0
Bank Sta=9749.115,10250.99
Exp/Cntr=0.3,0.1